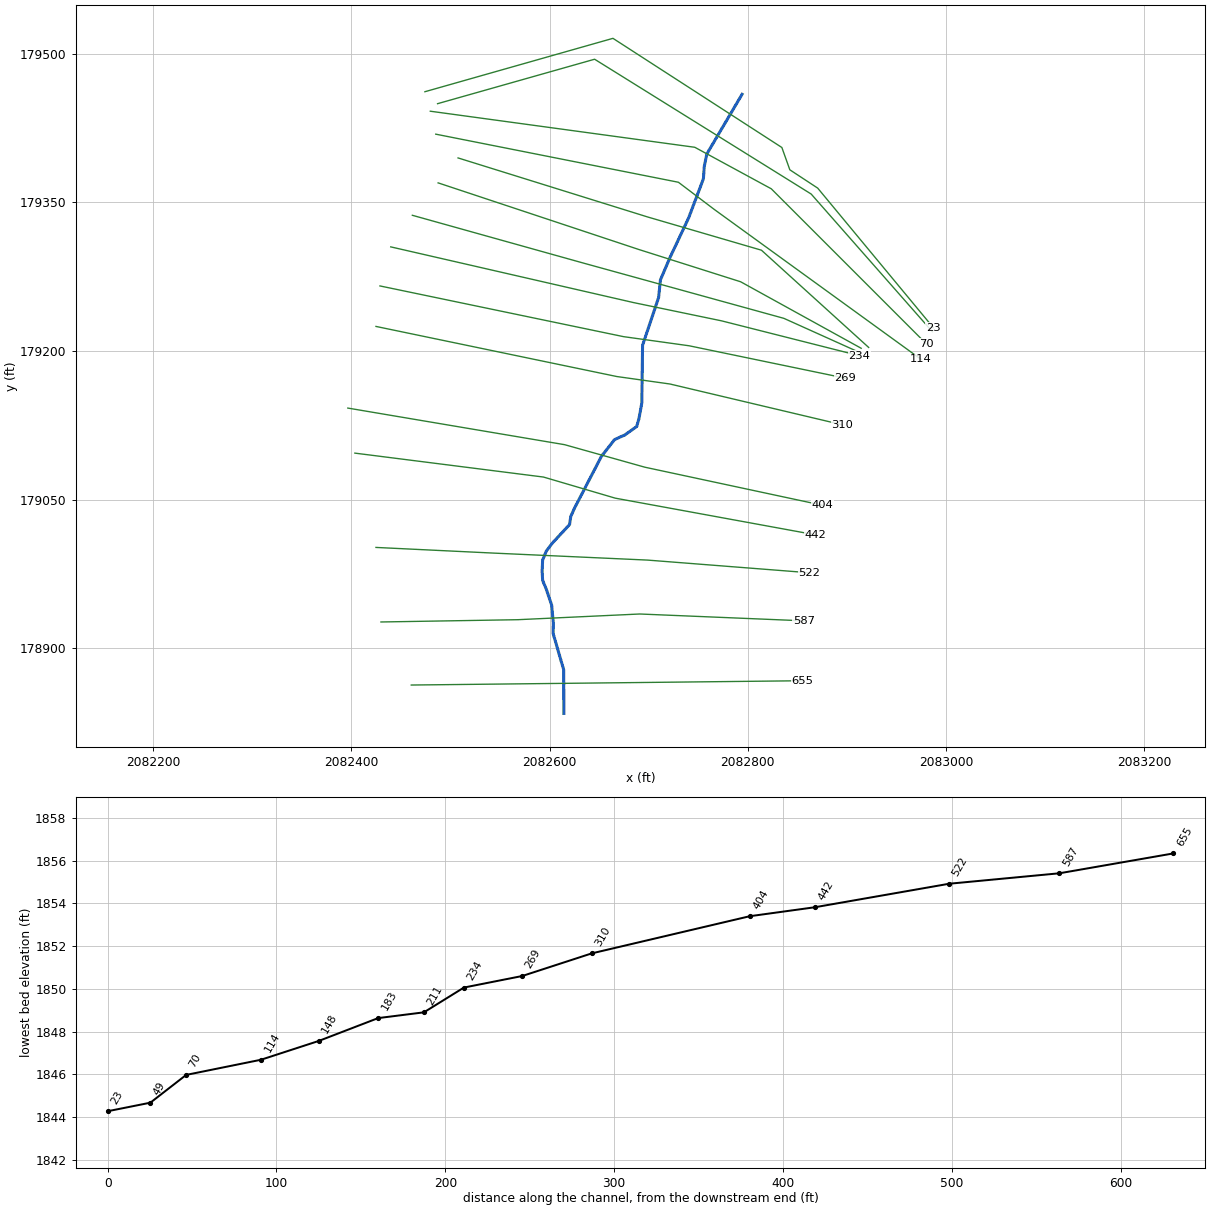
--- RCKCMPT1.prj (project) ---

Proj Title=RCKCMPT1
Current Plan=p01
Default Exp/Contr=0,0
English Units
Geom File=g01
Flow File=f01
Plan File=p01
Background Map Layer=Inundation Boundary (01pct Value_0)
BEGIN DESCRIPTION:
Stream Name: Rock Camp Creek Tributary
Flood Zone: Approximate
Monroe County, West Virginia
HEC-RAS Version: 5.0.7
Vertical Datum: NAVD88
Projection: NAD 1983 StatePlane West Virginia S FIPS 4702 (US Feet)
LiDAR: 2016, 1-meter
Land Use: 2016 NLCD
Hydrology Method:
Regression.
Model Notes:
END DESCRIPTION:
DSS Export Rating Curves= 0
DSS Export Rating Curve Sorted= 0
DSS Export Volume Flow Curves= 0
DXF OffsetX= 0
DXF OffsetY= 0
DXF ScaleX= 0
DXF ScaleY= 0

--- RCKCMPT1.p01 (plan) ---

Plan Title=Floodplain
Program Version=5.07
Short Identifier=Floodplain
Geom File=g01
Flow File=f01
Subcritical Flow
K Sum by GR= 0
Std Step Tol= 0.01
Critical Tol= 0.01
Num of Std Step Trials= 20
Max Error Tol= 0.3
Flow Tol Ratio= 0.001
Split Flow NTrial= 30
Split Flow Tol= 0.02
Split Flow Ratio= 0.02
Log Output Level= 0
Friction Slope Method= 1
Unsteady Friction Slope Method= 2
Unsteady Bridges Friction Slope Method= 1
Parabolic Critical Depth
Global Vel Dist= 0 , 0 , 0
Global Log Level= 0
CheckData=True
Encroach Param=-1 ,0,0, 0
Mapping Interval=1HOUR
Computation Time Step Use Courant=        0
Computation Time Step Use Time Series=    0
Computation Time Step Count To Double=0
Computation Time Step Max Doubling=0
Computation Time Step Max Halving=0
Computation Time Step Residence Courant=0
Run HTab= 0
Run UNet= 0
Run Sediment= 0
Run PostProcess= 0
Run WQNet= 0
Run RASMapper=-1
UNET Theta= 0
UNET Theta Warmup= 0
UNET ZTol= 0
UNET ZSATol= 0
UNET MxIter= 0
UNET Max Iter WO Improvement= 0
UNET MaxInSteps= 0
UNET DtIC= 0
UNET DtMin= 0
UNET MaxCRTS= 0
UNET WFStab= 0
UNET SFStab= 0
UNET WFX= 1
UNET SFX= 1
UNET 1D Methodology=Finite Difference
UNET DSS MLevel= 1
UNET Pardiso=0
UNET DZMax Abort= 0
UNET Use Existing IB Tables= 0
UNET Froude Reduction=False
UNET Froude Limit= 0
UNET Froude Power= 0
UNET D1 Cores= 0
UNET D2 Coriolis=0
UNET D2 Cores= 0
UNET D2 Theta= 1
UNET D2 Theta Warmup= 1
UNET D2 Z Tol= 0.01
UNET D2 Volume Tol= 0.01
UNET D2 Max Iterations= 20
UNET D2 Equation= 0
UNET D2 RampUpFraction=0.1
UNET D2 TimeSlices= 1
UNET D2 BCVolumeCheck=0
UNET D1D2 MaxIter= 0
UNET D1D2 ZTol=0.01
UNET D1D2 QTol=0.1
UNET D1D2 MinQTol=1
Write IC File= 0
Write IC File at Fixed DateTime=0
Write IC File at Sim End=0
Echo Input=False
Echo Parameters=False
Echo Output=False
Write Detailed= 0
HDF Write Warmup=0
HDF Write Time Slices=0
HDF Flush=0
HDF Face Node Velocities=0
HDF Compression= 1
HDF Chunk Size= 1
HDF Spatial Parts= 1
HDF Use Max Rows=0
HDF Fixed Rows= 1
Calibration Method= 0
Calibration Iterations= 20
Calibration Max Change=0.05
Calibration Tolerance=0.2
Calibration Maximum=1.5
Calibration Minimum=0.5
Calibration Optimization Method= 1
WQ AD Non Conservative
WQ ULTIMATE=-1
WQ Max Comp Step=1HOUR
WQ Output Interval=15MIN
WQ Output Selected Increments= 0
WQ Output face flow=0
WQ Output face velocity=0
WQ Output face area=0
WQ Output face dispersion=0
WQ Output cell volume=0
WQ Output cell surface area=0
WQ Output cell continuity=0
WQ Output cumulative cell continuity=0
WQ Output face conc=0
WQ Output face dconc_dx=0
WQ Output face courant=0
WQ Output face peclet=0
WQ Output face adv mass=0
WQ Output face disp mass=0
WQ Output cell mass=0
WQ Output cell source sink temp=0
WQ Output nsm pathways=0
WQ Output nsm derived pathways=0
WQ Output MaxMinRange=-1
WQ Daily Max Min Mean=-1
WQ Daily Range=0
WQ Daily Time=0
WQ Create Restart=0
WQ Fixed Restart=0
WQ System Summary=0
WQ Write To DSS=0
WQ Use Fixed Temperature=0
Sorting and Armoring Iterations= 10
XS Update Threshold= 0.02
Bed Roughness Predictor= 0
Hydraulics Update Threshold= 0.02
Energy Slope Method= 1
Volume Change Method= 1
Sediment Retention Method= 0
XS Weighting Method= 0
Number of US Weighted Cross Sections= 1
Number of DS Weighted Cross Sections= 1
Upstream XS Weight=0
Main XS Weight=1
Downstream XS Weight=0
Number of DS XS's Weighted with US Boundary= 1
Upstream Boundary Weight= 1
Weight of XSs Associated with US Boundary= 0
Number of US XS's Weighted with DS Boundary= 1
Downstream Boundary Weight= 0.5
Weight of XSs Associated with DS Boundary= 0.5
Percentile Method= 0
Sediment Output Level= 3
Mass or Volume Output= 0
Output Increment Type= 1
Profile and TS Output Increment= 1
XS Output Flag= 0
XS Output Increment= 10
Write Gradation File= 0
Read Gradation Hotstart= 0
Write HDF5 File= 1
Write Binary Output= 1
Write DSS Sediment File= 0
SV Curve= 0
Specific Gage Flag= 0

--- RCKCMPT1.f01 (steady flow) ---

Flow Title=Flow
Program Version=5.07
Number of Profiles= 6
Profile Names=01pct,10pct,04pct,02pct,0_2pct,01plus
River Rch & RM=RCKCMPT1,Main            ,655
     339     176     236     286     478     501
Boundary for River Rch & Prof#=RCKCMPT1,Main            , 1
Up Type= 0
Dn Type= 3
Dn Slope=0.04767
Boundary for River Rch & Prof#=RCKCMPT1,Main            , 2
Up Type= 0
Dn Type= 3
Dn Slope=0.04767
Boundary for River Rch & Prof#=RCKCMPT1,Main            , 3
Up Type= 0
Dn Type= 3
Dn Slope=0.04767
Boundary for River Rch & Prof#=RCKCMPT1,Main            , 4
Up Type= 0
Dn Type= 3
Dn Slope=0.04767
Boundary for River Rch & Prof#=RCKCMPT1,Main            , 5
Up Type= 0
Dn Type= 3
Dn Slope=0.04767
Boundary for River Rch & Prof#=RCKCMPT1,Main            , 6
Up Type= 0
Dn Type= 3
Dn Slope=0.04767
DSS Import GetInterval= 0
DSS Import GetPeak= 0
DSS Import FillOption= 0

--- RCKCMPT1.g01 (geometry) ---

Geom Title=Geometry
Program Version=5.07

River Reach=RCKCMPT1        ,Main
Reach XY= 30
     2082614.474      178834.242     2082614.335      178878.223
     2082603.665      178914.833     2082603.828      178925.942
     2082602.147      178943.614     2082596.672      178959.834
     2082593.059      178968.451     2082592.557      178977.813
     2082593.067      178988.927     2082596.734      178998.011
     2082603.188      179006.447     2082620.237      179024.776
     2082621.487      179033.126     2082625.507      179041.869
     2082652.413      179093.679     2082665.668      179110.557
     2082676.002       179115.24     2082688.008      179123.768
     2082690.304      179131.788     2082693.168      179147.453
     2082693.938       179205.77     2082710.146      179253.932
     2082711.934      179271.661     2082721.622       179294.38
     2082740.397      179334.255       2082752.7      179366.735
     2082755.355      179374.067     2082756.195      179386.228
     2082758.763      179398.764     2082794.356      179459.085

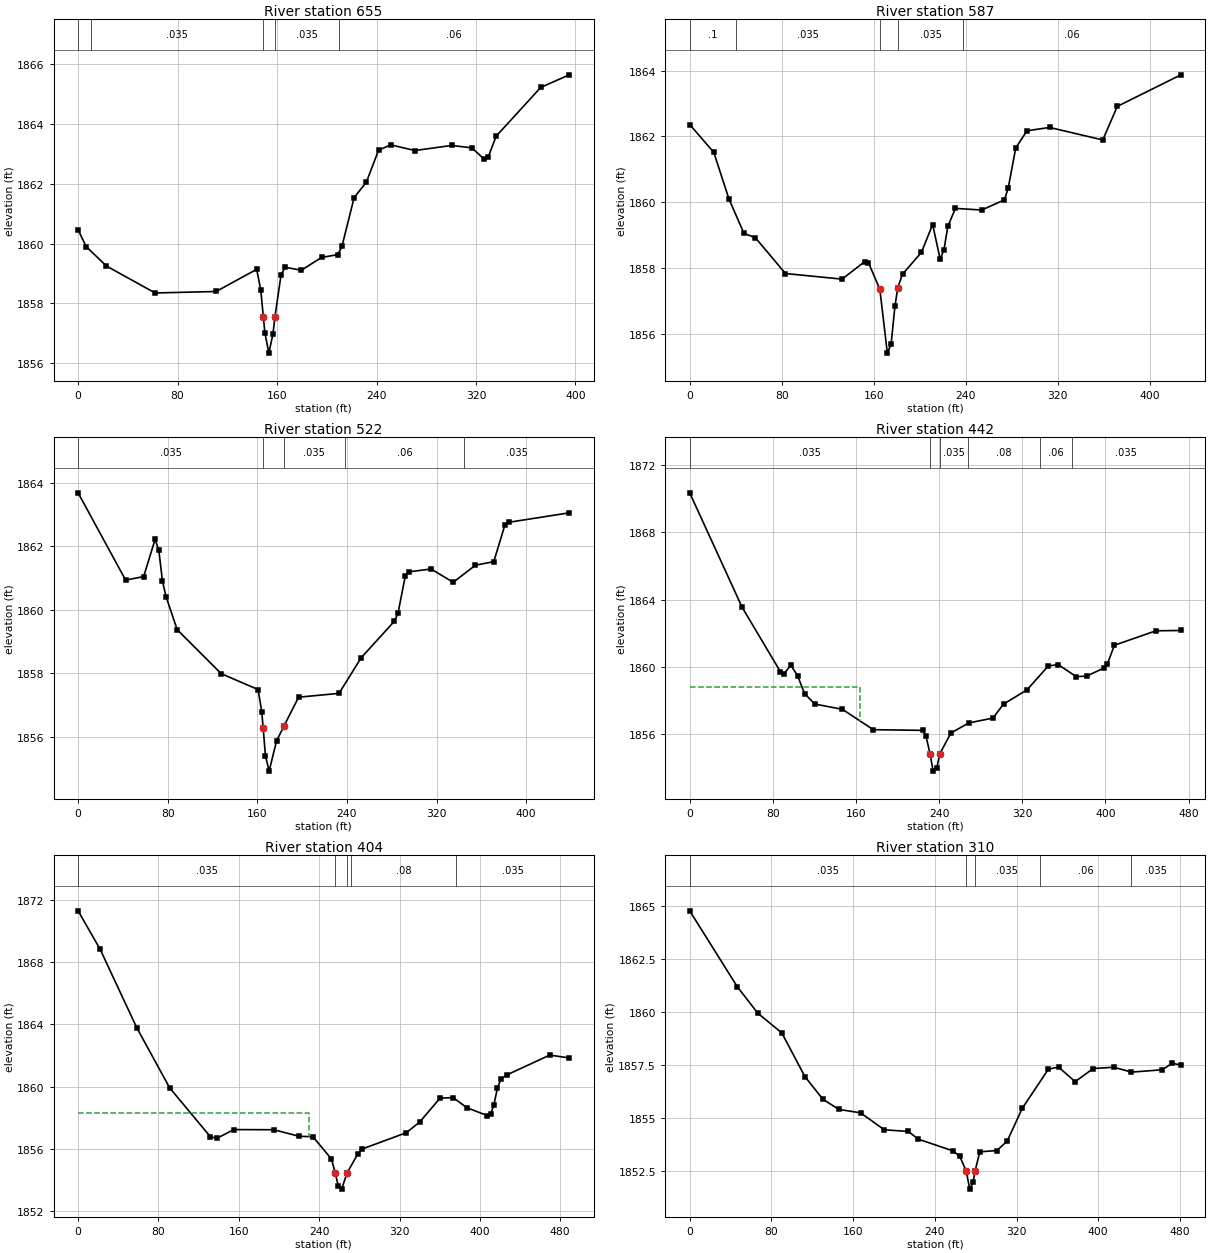
Type RM Length L Ch R = 1 ,655     ,67.2,67.5,67.6
XS GIS Cut Line= 2
     2082460.469      178862.848     2082855.435      178867.188
#Sta/Elev= 30
       0 1860.46     6.5  1859.9    22.8 1859.25      62 1858.35     111  1858.4
   143.6 1859.14   146.9 1858.45  148.971857.553   150.2 1857.02   153.4 1856.34
   156.7 1856.98   158.31857.552   163.2 1858.95   166.5 1859.21   179.5 1859.11
   195.9 1859.54   208.9 1859.63   212.2 1859.91     222 1861.54   231.8 1862.05
   241.6 1863.12   251.4  1863.3   270.9 1863.11   300.3 1863.28   316.6  1863.2
   326.4 1862.83   329.7 1862.88   336.2 1863.59   372.1 1865.22     395 1865.64
#Mann= 5 ,-1 , 0
       0      .1       0      10    .035       0  148.97    .045       0
   158.3    .035       0     210     .06       0
Bank Sta=148.97,158.3
XS Rating Curve= 0 ,0
Exp/Cntr=0.3,0.1

Type RM Length L Ch R = 1 ,587     ,65.6,65.3,63.8
XS GIS Cut Line= 4
2082429.86683089178926.4885734432082567.95368171178928.790020957
 2082691.0811237178934.543639741 2082856.7853447  178927.6392972
#Sta/Elev= 30
       0 1862.36      21 1861.51    34.1  1860.1    47.2 1859.05    57.1 1858.92
    83.3 1857.83   132.5 1857.66   152.2 1858.19   155.5 1858.16   165.4 1857.35
   171.9 1855.41   175.2 1855.69   178.5 1856.83     1811857.402   185.1 1857.81
   201.5 1858.47   211.3 1859.32   217.9 1858.26   221.2 1858.56   224.5 1859.26
   231.1 1859.81     254 1859.76   273.7 1860.07     277 1860.42   283.6 1861.65
   293.4 1862.17   313.1 1862.27   359.3 1861.89   371.9 1862.91   427.2 1863.87
#Mann= 5 ,-1 , 0
       0      .1       0      40    .035       0   165.4    .045       0
     181    .035       0  238.11     .06       0
Bank Sta=165.4,181
XS Rating Curve= 0 ,0
Exp/Cntr(USF)=0,0
Exp/Cntr=0.3,0.1

Type RM Length L Ch R = 1 ,522     ,82.7,79.5,74.4
XS GIS Cut Line= 4
2082424.86731842179001.7309577692082542.78098734178996.048371315
2082699.05211482178988.9451382472082862.42647537178976.159318726
#Sta/Elev= 30
       0 1863.69    42.4 1860.94    58.5 1861.05    68.7 1862.22      72 1861.89
    75.3 1860.91    78.5 1860.42    88.4 1859.38   127.8 1857.99   160.7 1857.49
   163.9 1856.79   165.2 1856.28   167.2 1855.41   170.5 1854.92   177.1 1855.87
   183.6 1856.33   196.8 1857.25   232.9 1857.37   252.6 1858.49   282.2 1859.64
   285.5 1859.89   292.1 1861.08   295.3  1861.2   315.1 1861.29   334.8 1860.87
   354.7 1861.41     371 1861.52   380.9 1862.67   384.2 1862.76   438.4 1863.06
#Mann= 5 ,-1 , 0
       0    .035       0   165.2    .045       0   183.6    .035       0
  238.05     .06       0  344.48    .035       0
Bank Sta=165.2,183.6
XS Rating Curve= 0 ,0
Exp/Cntr(USF)=0,0
Exp/Cntr=0.5,0.3

Type RM Length L Ch R = 1 ,442     ,38.2,38.6,39
XS GIS Cut Line= 4
2082403.55761922179096.9142808712082593.92426542179072.763288442
2082666.37724271 179051.453589242082868.10906182 179014.51677729
#Sta/Elev= 30
       0 1870.34    50.4 1863.55    87.3 1859.72    90.6 1859.59    97.3 1860.11
   103.9 1859.47   110.5 1858.42   120.4  1857.8   146.9 1857.49   176.6 1856.28
     224 1856.24   227.4 1855.88  231.211854.845   234.2 1853.82   237.7    1854
  240.541854.844   251.3 1856.08   268.4 1856.68   291.8 1856.97   301.9  1857.8
   324.4 1858.64   345.1 1860.07   354.7 1860.14   371.8 1859.43   381.8 1859.46
   398.5 1859.94   401.8 1860.17   408.5 1861.29   448.5 1862.15   472.5 1862.17
#Mann= 6 ,-1 , 0
       0    .035       0  231.21    .045       0  240.54    .035       0
  267.41     .08       0  337.41     .06       0  367.41    .035       0
#XS Ineff= 3 ,-1
       0  164.04 1858.82  212.75  226.36 1855.02  249.28   258.6 1854.98
Permanent Ineff=
       F       F       F
Bank Sta=231.21,240.54
XS Rating Curve= 0 ,0
Exp/Cntr(USF)=0,0
Exp/Cntr=0.5,0.3

Type RM Length L Ch R = 1 ,404     ,92,93.6,94.6
XS GIS Cut Line= 4
2082396.45438615179142.3749725022082615.23396462179105.438160552
2082696.21082159179082.7078147362082875.21229489179044.350356173
#Sta/Elev= 30
       0  1871.3    21.9 1868.83    58.5 1863.77    91.2 1859.91   131.7 1856.77
   138.3 1856.67     155 1857.23   194.9 1857.22   219.9  1856.8   233.8 1856.77
   252.2 1855.34  256.151854.416     259  1853.6   262.4  1853.4  267.621854.416
   278.4 1855.66   282.8 1855.98   326.8 1857.03   340.2 1857.72   360.3 1859.25
   373.3 1859.29   387.2 1858.63   407.5 1858.13   410.7 1858.23     414 1858.83
   417.4 1859.88   420.8 1860.46   426.6 1860.74   469.5 1862.02     489 1861.84
#Mann= 5 ,-1 , 0
       0    .035       0  256.15    .045       0  267.62    .035       0
  271.88     .08       0  375.98    .035       0
#XS Ineff= 3 ,-1
       0  229.94 1858.28  247.13  252.87 1854.56  272.92  284.38 1854.66
Permanent Ineff=
       F       F       F
Bank Sta=256.15,267.62
XS Rating Curve= 0 ,0
Exp/Cntr(USF)=0,0
Exp/Cntr=0.5,0.3

Type RM Length L Ch R = 1 ,310     ,41.2,41.2,41
XS GIS Cut Line= 4
2082424.86731842179224.7724760832082667.94609118179174.210966993
2082721.63425878179166.6610684242082895.28192587179125.556065103
#Sta/Elev= 30
       0 1864.79    46.6 1861.21    66.7 1859.96    90.2 1859.03   112.8 1856.97
   130.4  1855.9   146.1 1855.42   167.3 1855.26   190.5 1854.46   214.2 1854.38
   223.7 1854.02   257.4 1853.47   264.3 1853.22  270.731852.515   274.2 1851.66
   277.5 1851.98  279.381852.515   284.1 1853.42   300.7 1853.48   310.8 1853.92
   325.6 1855.47   351.2 1857.32   361.1 1857.42   377.4 1856.73   395.1 1857.35
   415.3 1857.41   432.5 1857.18   462.5 1857.29   472.6  1857.6   480.9 1857.51
#Mann= 5 ,-1 , 0
       0    .035       0  270.73    .045       0  279.38    .035       0
   342.5     .06       0   432.5    .035       0
Bank Sta=270.73,279.38
XS Rating Curve= 0 ,0
Exp/Cntr(USF)=0,0
Exp/Cntr=0.3,0.1

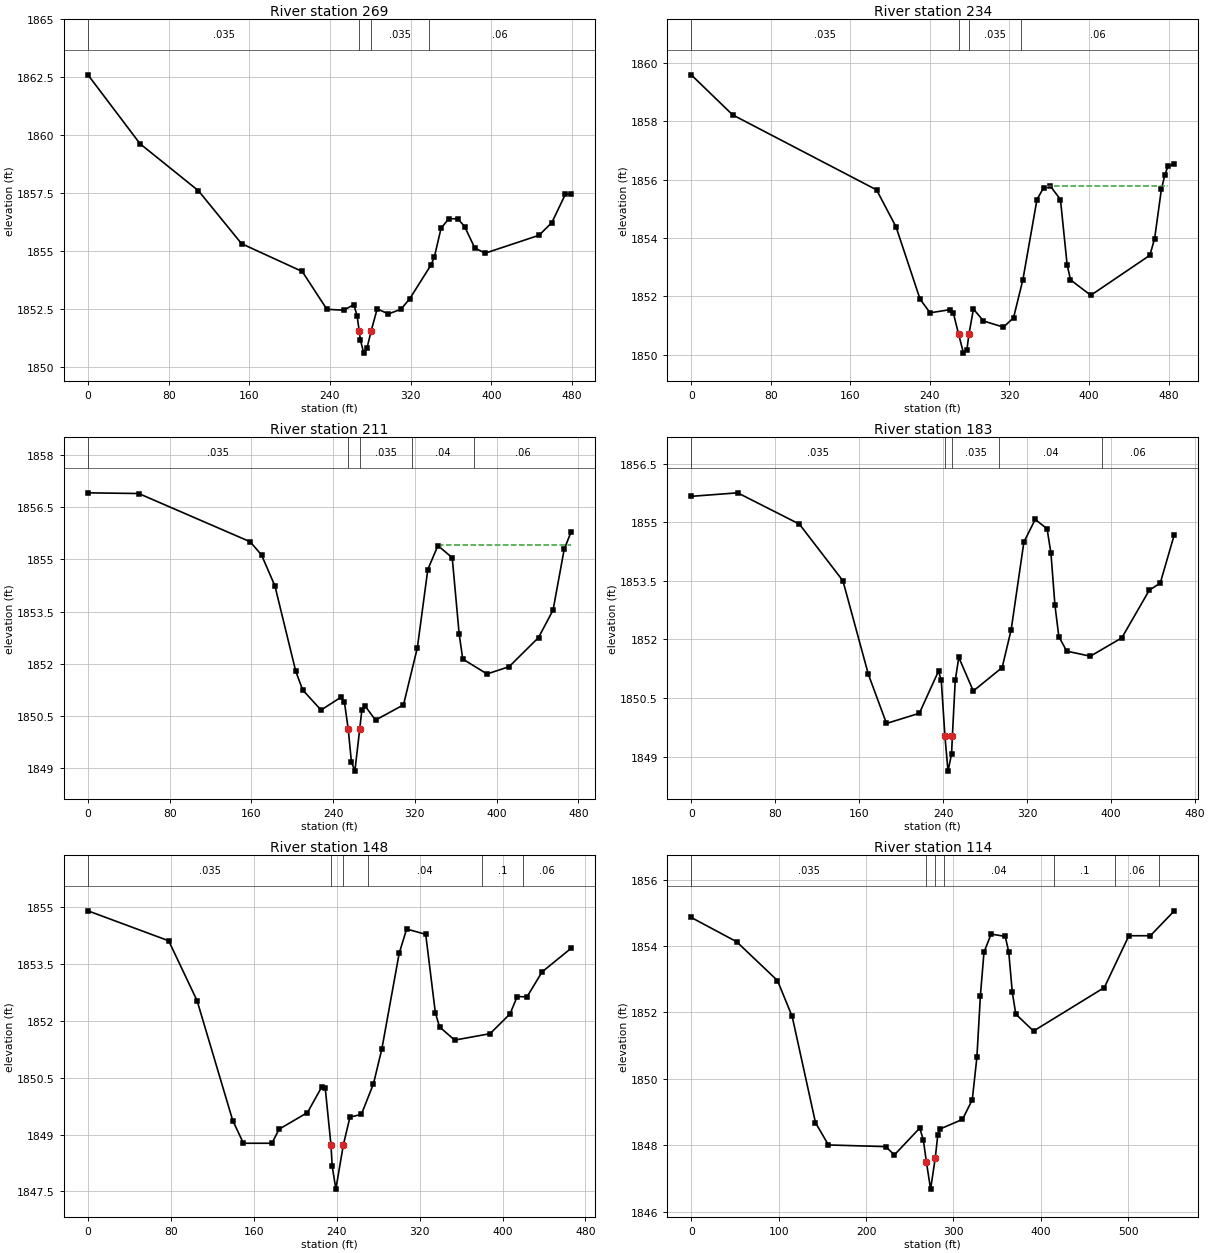
Type RM Length L Ch R = 1 ,269     ,35.3,34.5,33.2
XS GIS Cut Line= 4
2082428.86596982 179265.648627442082674.65711213179214.477092694
2082740.92844401179205.2494388882082898.63743634179172.533211755
#Sta/Elev= 30
       0  1862.6    51.6 1859.63   109.6  1857.6   152.3 1855.32   212.5 1854.12
   236.9 1852.49   253.6 1852.45   263.6 1852.69   266.9 1852.21  268.951851.555
   270.2 1851.16   273.5  1850.6   276.8 1850.84  280.831851.556   286.8 1852.51
   297.9 1852.29   310.3 1852.49     319 1852.94     340 1854.39   343.4 1854.73
   350.1 1855.98   357.8  1856.4   366.8 1856.39   373.5 1856.06   383.6 1855.13
   393.9 1854.91   447.2 1855.68     460 1856.23   473.5 1857.46     479 1857.44
#Mann= 4 ,-1 , 0
       0    .035       0  268.95    .045       0  280.83    .035       0
  337.97     .06       0
#XS Ineff= 2 , 0
          264.33 1851.65  285.82         1851.65
Permanent Ineff=
       F       F
Bank Sta=268.95,280.83
XS Rating Curve= 0 ,0
Exp/Cntr(USF)=0,0
Exp/Cntr=0.5,0.3

Type RM Length L Ch R = 1 ,234     ,24.6,23.7,22.7
XS GIS Cut Line= 4
2082439.77137887179305.0758755232082684.72364355179248.871075064
2082773.64467114179230.4157674512082912.89835586179195.182907462
#Sta/Elev= 30
       0 1859.59    41.6 1858.22   186.4 1855.65     206 1854.38   230.1 1851.91
   240.2 1851.44   260.4 1851.55   263.7 1851.42  268.781850.721   273.8 1850.06
   277.1 1850.15  279.34 1850.72   283.8 1851.57   293.9 1851.16     314 1850.95
   324.1 1851.27   333.5 1852.57   347.7 1855.32   354.3 1855.72   361.1 1855.78
   371.3 1855.32     378 1853.09   381.4 1852.57   401.8 1852.04   461.2 1853.41
     466 1853.98   472.8 1855.67   476.2 1856.15   479.5 1856.47   485.8 1856.52
#Mann= 4 ,-1 , 0
       0    .035       0  268.78    .045       0  279.34    .035       0
  331.32     .06       0
#XS Ineff= 3 ,-1
       0  264.33 1850.75  283.67  328.08 1850.75  357.45  479.94  1855.8
Permanent Ineff=
       F       F       F
Bank Sta=268.78,279.34
XS Rating Curve= 0 ,0
Exp/Cntr(USF)=0,0
Exp/Cntr=0.5,0.3

Type RM Length L Ch R = 1 ,211     ,27.7,27.1,26.5
XS GIS Cut Line= 4
2082461.58219696179336.9532250372082632.71323119179289.137200766
2082836.56049255179232.9324003082082912.89835586179198.538417937
#Sta/Elev= 30
       0 1856.92    49.7  1856.9   158.8 1855.51   169.9 1855.13     183 1854.24
   203.4 1851.78   210.2 1851.24   228.2 1850.66   247.7 1851.03   251.1 1850.88
  254.81 1850.11   257.9 1849.17   261.3  1848.9  266.041850.109   268.1 1850.65
   271.5 1850.77   281.5 1850.37   308.9 1850.81   322.5 1852.46   332.7 1854.71
   342.6  1855.4   356.6 1855.05   363.4 1852.85   366.9 1852.13   390.7  1851.7
   412.3 1851.91   441.1 1852.75   455.3 1853.54   466.2 1855.29   472.9 1855.79
#Mann= 5 ,-1 , 0
       0    .035       0  254.81    .045       0  266.04    .035       0
  317.69     .04       0  377.69     .06       0
#XS Ineff= 2 , 0
                          345.27         1855.43
Permanent Ineff=
       F       F
Bank Sta=254.81,266.04
XS Rating Curve= 0 ,0
Exp/Cntr(USF)=0,0
Exp/Cntr=0.5,0.3

Type RM Length L Ch R = 1 ,183     ,34.8,35.2,36.5
XS GIS Cut Line= 4
2082487.58740314179369.6694521692082689.75690927179302.559242667
2082792.93885638179269.843015534 2082914.5761111179202.732806031
#Sta/Elev= 30
       0 1855.66    44.2 1855.75     103 1854.95   144.5  1853.5   168.7 1851.11
     186 1849.85   217.3 1850.11   235.6 1851.19   238.2 1850.95   241.71849.521
   244.6 1848.63     248 1849.07  248.771849.521   251.5 1850.95   254.9 1851.54
   268.7 1850.68   296.2 1851.28   304.8 1852.25   316.9 1854.49   327.7 1855.07
     339 1854.83   342.7  1854.2   346.5 1852.87   350.2 1852.07   357.7  1851.7
   380.2 1851.57   410.2 1852.04   436.4 1853.26   446.8 1853.44   460.2 1854.68
#Mann= 5 ,-1 , 0
       0    .035       0   241.7    .045       0  248.77    .035       0
  293.02     .04       0  391.26     .06       0
#XS Ineff= 2 ,-1
  233.05  234.24 1849.66   254.3   460.2 1849.74
Permanent Ineff=
       F       F
Bank Sta=241.7,248.77
XS Rating Curve= 0 ,0
Exp/Cntr(USF)=0,0
Exp/Cntr=0.5,0.3

Type RM Length L Ch R = 1 ,148     ,39.8,34.2,28.5
XS GIS Cut Line= 4
2082507.72046599179394.8357807332082698.98456307179335.275469799
2082813.91079685179301.7203650482082922.12600967 179203.57168365
#Sta/Elev= 30
       0  1854.9    77.9 1854.11   105.3 1852.53   139.7 1849.37     150 1848.77
   177.5 1848.77   184.4 1849.14   211.8 1849.58   225.5 1850.25   228.9 1850.24
  234.46 1848.73   235.7 1848.16   239.2 1847.56   246.41848.724   252.8 1849.46
   263.8 1849.53   275.5 1850.34   283.6 1851.26   300.3 1853.78   307.5 1854.42
   325.9 1854.28   335.2 1852.21   339.2 1851.84   353.8 1851.49     388 1851.66
   407.2 1852.18   414.2 1852.64   423.6 1852.63   438.2 1853.29   466.1 1853.91
#Mann= 6 ,-1 , 0
       0    .035       0  234.46    .045       0   246.4    .035       0
  270.32     .04       0  380.05      .1       0  420.05     .06       0
#XS Ineff= 2 ,-1
  224.58  227.79 1848.93  252.15   466.1 1848.96
Permanent Ineff=
       F       F
Bank Sta=234.46,246.4
XS Rating Curve= 0 ,0
Exp/Cntr(USF)=0,0
Exp/Cntr=0.5,0.3

Type RM Length L Ch R = 1 ,114     ,41.6,44.3,47.5
XS GIS Cut Line= 4
2082485.20236813179418.8311534152082730.09478436179370.293917767
 2082766.4977111179342.7159429662082974.98720059 179191.58864106
#Sta/Elev= 30
       0 1854.86    51.9 1854.13    98.7 1852.96   115.5 1851.88   142.2 1848.68
     157 1848.01   222.5 1847.96   232.5 1847.71   261.5 1848.52   265.6 1848.16
   269.11847.499   273.9 1846.68   279.31847.628   282.1  1848.3   284.7 1848.49
   310.4 1848.78   321.6 1849.37   326.9 1850.65   330.9 1852.51     335 1853.81
   343.1 1854.36   359.3 1854.29   363.3 1853.83   367.4 1852.61   371.4 1851.95
   391.7 1851.44   472.7 1852.75   500.8 1854.31   525.4 1854.31   552.8 1855.06
#Mann= 7 ,-1 , 0
       0    .035       0   269.1    .045       0   279.3    .035       0
  289.66     .04       0  415.33      .1       0  485.33     .06       0
  535.33    .035       0
Bank Sta=269.1,279.3
XS Rating Curve= 0 ,0
Exp/Cntr(USF)=0,0
Exp/Cntr=0.3,0.1

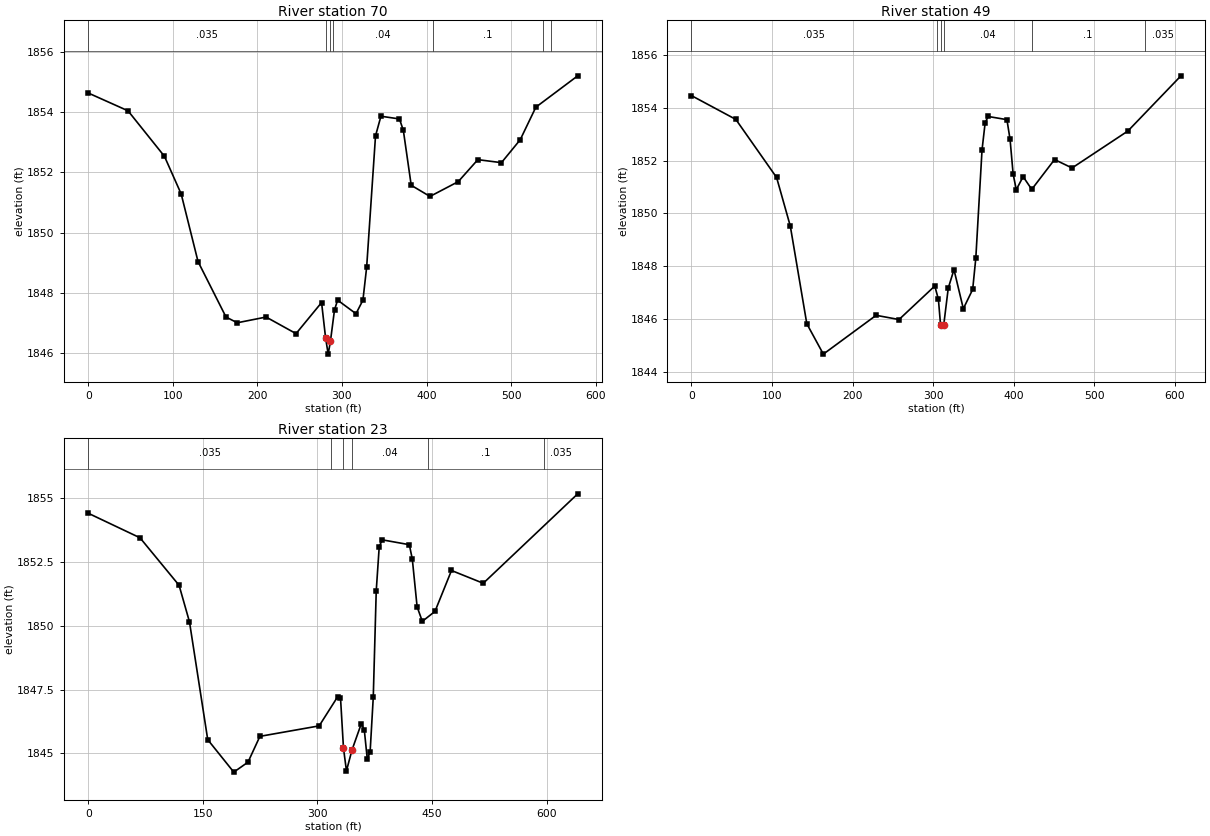
Type RM Length L Ch R = 1 ,70      ,22.1,21.2,20.6
XS GIS Cut Line= 4
2082479.68677317179441.9966522482082746.64156924179405.593725511
2082823.85989868179363.6752038152082980.50279555179207.032306949
#Sta/Elev= 30
       0 1854.63      47 1854.04    90.1 1852.53   109.9 1851.28   129.8 1849.04
   162.9  1847.2   176.2 1847.01   210.3  1847.2   245.7 1846.65   275.9 1847.68
   280.6 1846.52   283.7 1845.97   286.4  1846.4   291.2 1847.44   294.9 1847.76
   316.6 1847.31   324.8 1847.76   329.2 1848.85   339.7 1853.21   346.1 1853.86
     368 1853.77   372.6 1853.39   381.9 1851.57   404.1  1851.2   437.5 1851.69
   460.7 1852.42   488.6 1852.32   510.8 1853.08   529.3 1854.16   578.8  1855.2
#Mann= 7 ,-1 , 0
       0    .035       0   280.6    .045       0   286.4    .035       0
  289.43     .04       0  407.29      .1       0  537.29     .06       0
  547.29    .035       0
Bank Sta=280.6,286.4
XS Rating Curve= 0 ,0
Exp/Cntr(USF)=0,0
Exp/Cntr=0.3,0.1

Type RM Length L Ch R = 1 ,49      ,25.6,25.3,25.1
XS GIS Cut Line= 4
 2082487.0231045179449.5908245212082645.52574968179494.463719502
2082864.10017362179358.3975218182082986.41500026179219.436298651
#Sta/Elev= 30
       0 1854.46      55 1853.56   105.6 1851.36   122.6 1849.52   143.1 1845.82
   163.6 1844.67   229.1 1846.14   257.5 1845.98   301.9 1847.25   306.4 1846.74
  309.09 1845.76  312.93 1845.76   318.6 1847.17   325.7 1847.87   337.3 1846.39
   348.9 1847.12   352.8 1848.31   360.5  1852.4   364.4 1853.44   368.2 1853.67
   391.4 1853.55   395.3  1852.8   399.1 1851.49     403  1850.9   411.5 1851.39
   422.2 1850.91   450.5 1852.04   472.2 1851.72   541.5 1853.12607.3229 1855.21
#Mann= 6 ,-1 , 0
       0    .035       0  304.73     .04       0  309.09    .045       0
  312.93     .04       0   422.2      .1       0   562.2    .035       0
Bank Sta=309.09,312.93
XS Rating Curve= 0 ,0
Exp/Cntr(USF)=0,0
Exp/Cntr=0.3,0.1

Type RM Length L Ch R = 1 ,23      ,,,
XS GIS Cut Line= 6
2082474.24879391179461.6688399022082664.03379778179515.548480829
2082834.51863175179405.3766777392082842.56036921179382.859812874
2082870.70645029179364.3638167352082987.31675859179223.612067802
#Sta/Elev= 30
       0  1854.4    67.7 1853.44   118.9 1851.58   132.5 1850.15   156.4 1845.54
   190.5 1844.27   209.1 1844.66   224.7 1845.67   302.3 1846.08   326.5 1847.22
   330.2 1847.19   334.1 1845.21     338 1844.32   345.3 1845.14   357.5 1846.17
   361.4 1845.91   365.3 1844.77     369 1845.07   373.1  1847.2     377 1851.37
   380.9 1853.09   384.8 1853.36   420.3 1853.17   424.2 1852.61   430.5 1850.74
   437.3 1850.17   453.9 1850.56   475.5 1852.16   517.1 1851.66 640.747 1855.16
#Mann= 6 ,-1 , 0
       0    .035       0  317.28     .04       0   334.1    .045       0
   345.3     .04       0  444.18      .1       0  597.16    .035       0
Bank Sta=334.1,345.3
XS Rating Curve= 0 ,0
Exp/Cntr(USF)=0,0
Exp/Cntr=0.3,0.1
LCMann Table=0

Chan Stop Cuts=-1
Use User Specified Reach Order=0
Composite Channel Slope=5